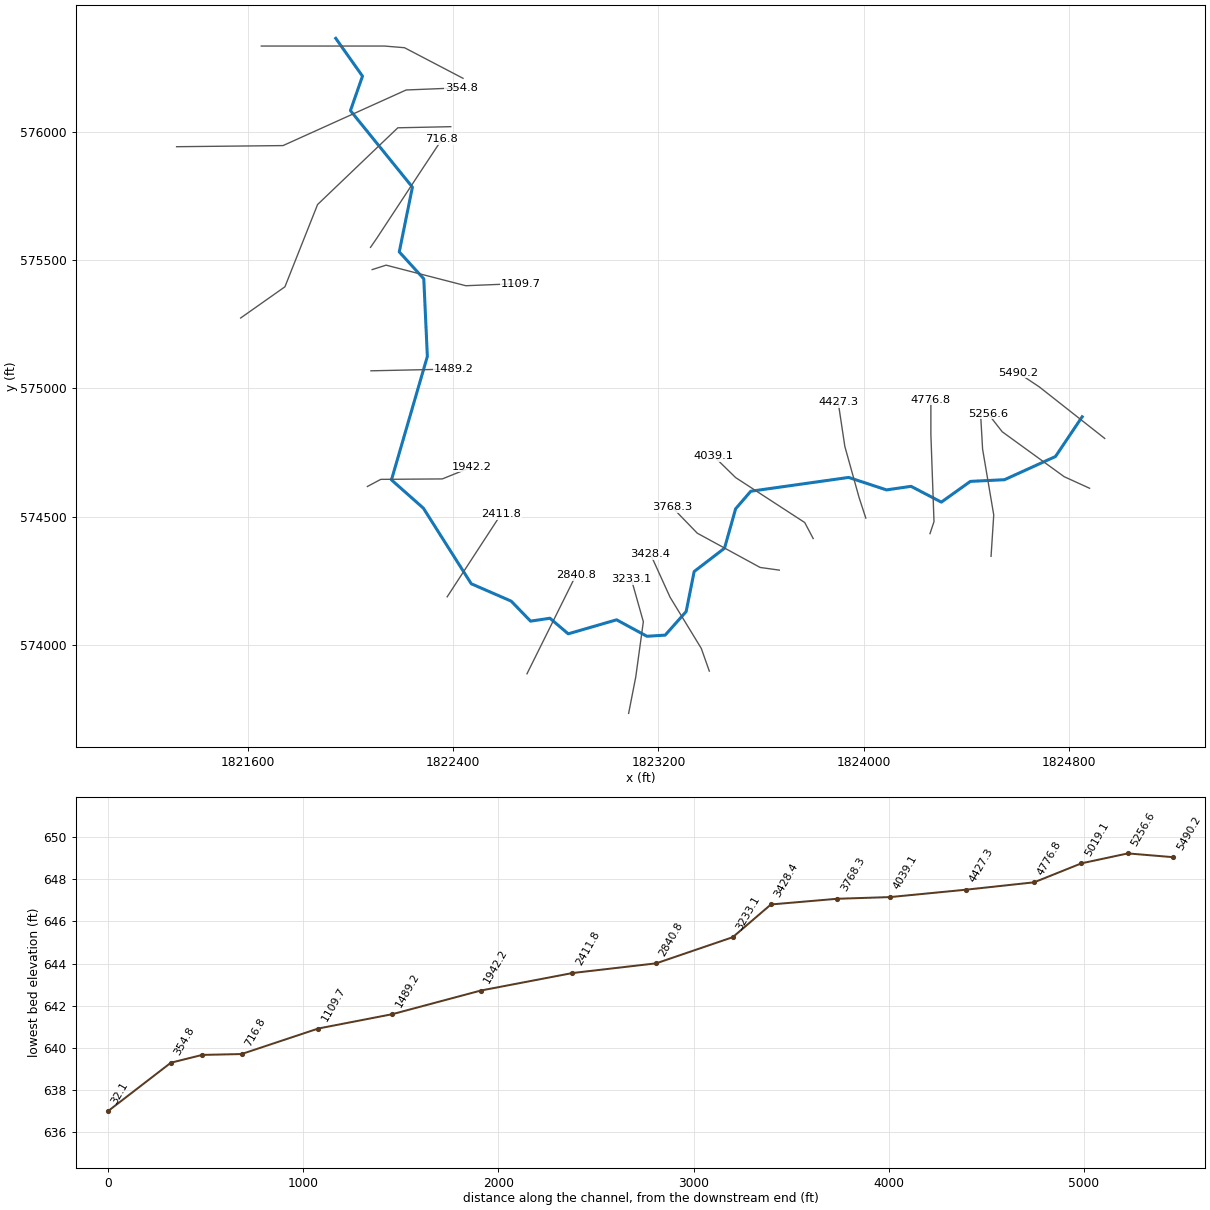
--- GREENCK.prj (project) ---

Proj Title=GREENCK
Current Plan=p01
Default Exp/Contr=0,0
English Units
Geom File=g01
Flow File=f01
Plan File=p01
BEGIN DESCRIPTION:
END DESCRIPTION:
DSS Export Rating Curves= 0
DSS Export Rating Curve Sorted= 0
DSS Export Volume Flow Curves= 0
DXF OffsetX= 0
DXF OffsetY= 0
DXF ScaleX= 0
DXF ScaleY= 0

--- GREENCK.p01 (plan) ---

Plan Title=Floodplain
Program Version=4.00
Geom File=g01
Flow File=f01
K Sum by GR=0
Std Step Tol=0.01
Critical Tol=0.01
Num of Std Step Trials=20
Max Error Tol=0.3
Flow Tol Ratio=0.001
Split Flow NTrial=30
Split Flow Tol=0.02
Split Flow Ratio=0.02
Log Output Level=0
Friction Slope Method=1
Unsteady Friction Slope Method=2
Unsteady Bridges Friction Slope Method=1
Global Log Level=0
CheckData=False
Run HTab=0
Run UNet=0
Run PostProcess=0
UNET Theta=0
UNET Theta Warmup=0
UNET ZTol=0
UNET ZSATol=0
UNET MxIter=0
UNET MaxInSteps=0
UNET DtIC=0
UNET DtMin=0
UNET MaxCRTS=0
UNET WFStab=0
UNET SFStab=0
UNET WFX=0
UNET SFX=0
UNET DSS MLevel=0
UNET DZMax Abort=0
UNET Convert EG Bridges=0
UNET Use Existing IB Tables=0
UNET Froude Limit=0
UNET Froude Power=0
Write IC File=0
Echo Input=False
Echo Output=False
Write Detailed=0

--- GREENCK.f01 (steady flow) ---

Flow Title=NFF Regression Equation
Program Version=4.10
Number of Profiles= 1
Profile Names=P100yr
River Rch & RM=GREENCK,Main            ,5490.2
3335.438
River Rch & RM=GREENCK,Main            ,515.6
3514.438
Boundary for River Rch & Prof#=GREENCK,Main            , 1
Up Type= 0
Dn Type= 3
Dn Slope=0.007
DSS Import GetInterval= 0
DSS Import GetPeak= 0
DSS Import FillOption= 0

--- GREENCK.g01 (geometry) ---

Geom Title=USGS 10m DEM
Program Version=4.10

River Reach=GREENCK         ,Main
Reach XY= 30
     1824850.149      574889.158     1824746.244      574734.046
     1824547.728      574643.601     1824414.915      574637.091
       1824301.8      574556.094     1824183.744      574617.726
     1824088.258      574603.837     1823940.689      574652.448
     1823559.612      574598.629     1823500.585      574530.053
     1823457.319      574376.295     1823339.126      574285.261
     1823307.876      574129.011     1823226.279      574036.997
     1823155.099      574032.657     1823037.043      574096.893
     1822848.675      574042.205     1822777.494      574102.969
     1822701.974      574091.684     1822626.453      574169.809
     1822471.071      574237.518     1822284.439      574532.657
     1822160.307        574642.9     1822300.064      575124.671
     1822286.175      575427.622     1822190.689      575532.657
     1822241.904      575785.261     1822000.585      576083.872
      1822047.46      576218.421     1821943.293       576365.99

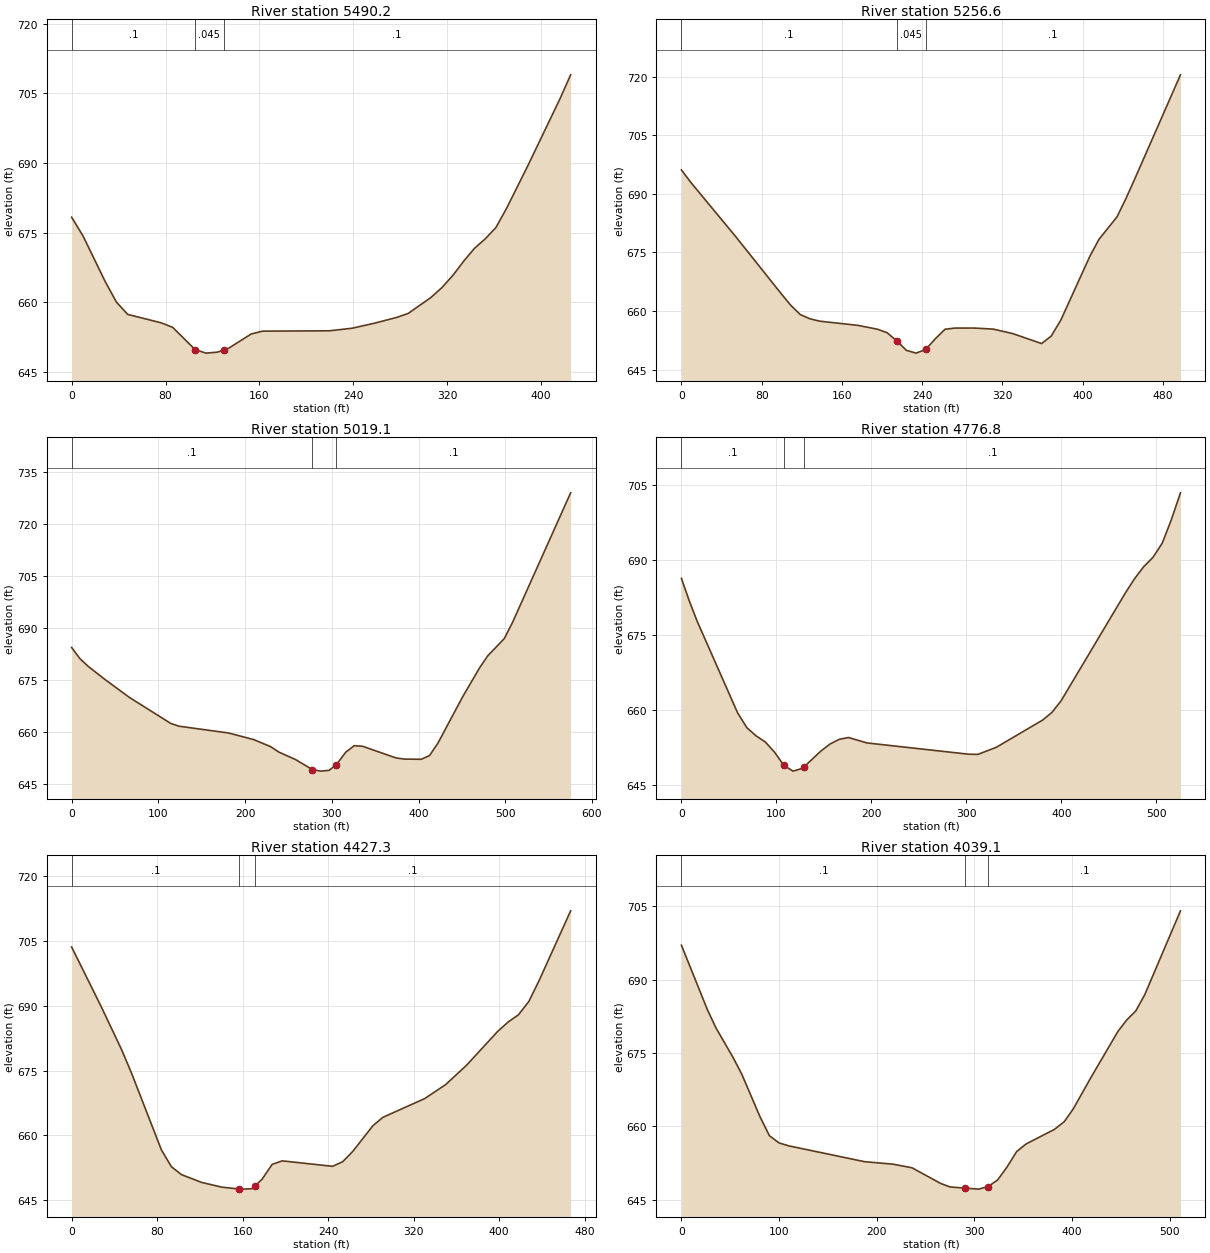
Type RM Length L Ch R = 1 ,5490.2  ,228.6,233.5,241.4
XS GIS Cut Line= 3
     1824938.085      574804.647     1824682.876      575006.036
     1824599.543      575061.592
#Sta/Elev= 30
       0   678.3     9.6  674.33    28.7  664.41    38.2  660.02    47.8  657.38
    76.5  655.55    86.1  654.59   105.2  649.81   114.5  649.04   124.3  649.25
   129.5  649.72   133.9  650.11     153  653.16   162.6  653.77   219.9  653.85
     239   654.4   258.2  655.49   277.3  656.75   286.8  657.59     306  660.99
   315.5  663.14   325.1  665.86   334.2  668.88   343.3  671.61   352.4  673.64
   361.5  676.07   370.6  680.21   388.8  689.43   416.2  703.85   425.2  708.96
#Mann= 3 , 0 , 0
       0      .1       0   105.2    .045       0   129.5      .1       0
Bank Sta=105.2,129.5
XS Rating Curve= 0 ,0
Exp/Cntr=0.3,0.1

Type RM Length L Ch R = 1 ,5256.6  ,258.6,237.6,212.3
XS GIS Cut Line= 4
     1824879.057      574610.203     1824780.099      574655.342
     1824538.779      574830.689     1824483.224       574901.87
#Sta/Elev= 30
       0  696.12     9.1  693.02    54.4  678.96    99.7  664.36   108.8  661.52
   118.4   659.1     128  658.02   137.6  657.41   176.1  656.32   195.4  655.34
     205  654.45   214.6  652.36   224.2  649.94   233.9  649.22   243.5  650.17
   253.1  652.91   262.7  655.33   272.4  655.63   291.6  655.64   310.8  655.37
   330.1  654.23     359  651.67   368.6  653.59   378.2   657.7   407.1  674.02
   416.1  678.33   434.2  684.13   443.2  688.88   452.2  694.03   497.4  720.48
#Mann= 3 , 0 , 0
       0      .1       0   214.6    .045       0   243.5      .1       0
Bank Sta=214.6,243.5
XS Rating Curve= 0 ,0
Exp/Cntr=0.3,0.1

Type RM Length L Ch R = 1 ,5019.1  ,245,242.3,239.1
XS GIS Cut Line= 4
     1824495.376      574344.578     1824505.793      574506.036
      1824462.39      574762.981      1824453.71      574915.759
#Sta/Elev= 30
       0  684.38     9.5  681.18      19  678.96    38.1  675.22    66.6  669.99
   114.2  662.51   123.7   661.7   181.1  659.73     210  657.83   229.4  655.81
     239  654.23   258.3  652.07   277.6   649.2   287.3  648.75   296.9  648.98
   305.4  650.64   316.2  654.23   325.9  656.09   335.5  655.91   374.1  652.55
   383.8  652.22   403.1  652.16   412.7  653.23   422.4  656.83   451.1  670.26
   470.2  678.43   479.8  681.97   498.9  686.95   508.4   691.6   575.4  728.93
#Mann= 3 , 0 , 0
       0      .1       0   277.6    .045       0   305.4      .1       0
Bank Sta=277.6,305.4
XS Rating Curve= 0 ,0
Exp/Cntr=0.3,0.1

Type RM Length L Ch R = 1 ,4776.8  ,343,349.5,354.8
XS GIS Cut Line= 4
     1824257.529       574433.12     1824273.154      574479.995
     1824261.001      574820.272     1824261.001      574955.689
#Sta/Elev= 30
       0  686.39     8.2  681.94    16.5  677.85    59.1  659.52    68.9  656.53
    78.6   654.9    88.3  653.68      98  651.65   107.8     649   117.5  647.85
   127.2  648.39   129.1  648.71   146.7  651.85   156.4  653.27   166.2  654.22
   175.9  654.57   195.3  653.49   302.4  651.23   312.1   651.2   331.5  652.62
   380.2  658.06   389.9  659.57   399.6   661.9   467.3  683.49     477  686.34
   486.6  688.73   496.3  690.59     506   693.4   515.6  698.07   525.3  703.51
#Mann= 3 , 0 , 0
       0      .1       0   107.8    .045       0   129.1      .1       0
Bank Sta=107.8,129.1
XS Rating Curve= 0 ,0
Exp/Cntr=0.3,0.1

Type RM Length L Ch R = 1 ,4427.3  ,364.7,388.2,411.4
XS GIS Cut Line= 4
     1824007.529      574493.884     1823981.487      574573.745
     1823925.932      574773.397      1823899.89      574947.009
#Sta/Elev= 30
       0  703.64      28  689.65    46.7  679.86      56  674.42      84  656.59
    93.4  652.68   102.8  650.86   121.7  649.05   140.5  647.96   156.9  647.52
   159.4   647.5   168.8  647.59   171.9  648.32   178.2  649.81   187.6  653.24
     197  654.05   244.1  652.79   253.6  653.86     263  656.25   281.8  662.19
   291.2  664.15   330.2  668.48   349.8  671.72   369.3  676.19   398.5  684.05
   408.3  686.24     418  687.92   427.8  691.05   437.5  695.96   466.8  712.02
#Mann= 3 , 0 , 0
       0      .1       0   156.9    .045       0   171.9      .1       0
Bank Sta=156.9,171.9
XS Rating Curve= 0 ,0
Exp/Cntr=0.3,0.1

Type RM Length L Ch R = 1 ,4039.1  ,275.9,270.8,265.9
XS GIS Cut Line= 4
     1823802.668      574414.022     1823769.682      574476.522
     1823500.585       574651.87     1823415.515      574735.203
#Sta/Elev= 30
       0  697.02    26.5  683.88    35.3  680.14      53  674.02    61.8  670.64
    80.4  661.97    90.1  658.07    99.9   656.6   109.6  656.01   187.5  652.76
   216.7  652.25   236.1  651.51   265.3  648.32   275.1  647.59   290.8  647.35
   304.3  647.15     314  647.68   323.7  649.02   333.5  651.72   343.2  654.84
   352.9  656.39   382.1  659.39   391.9  660.94     401  663.51   419.3  669.99
   446.8  679.37     456  681.76   465.1  683.57   474.3  686.88   510.9  704.05
#Mann= 3 , 0 , 0
       0      .1       0   290.8    .045       0     314      .1       0
Bank Sta=290.8,314
XS Rating Curve= 0 ,0
Exp/Cntr=0.3,0.1

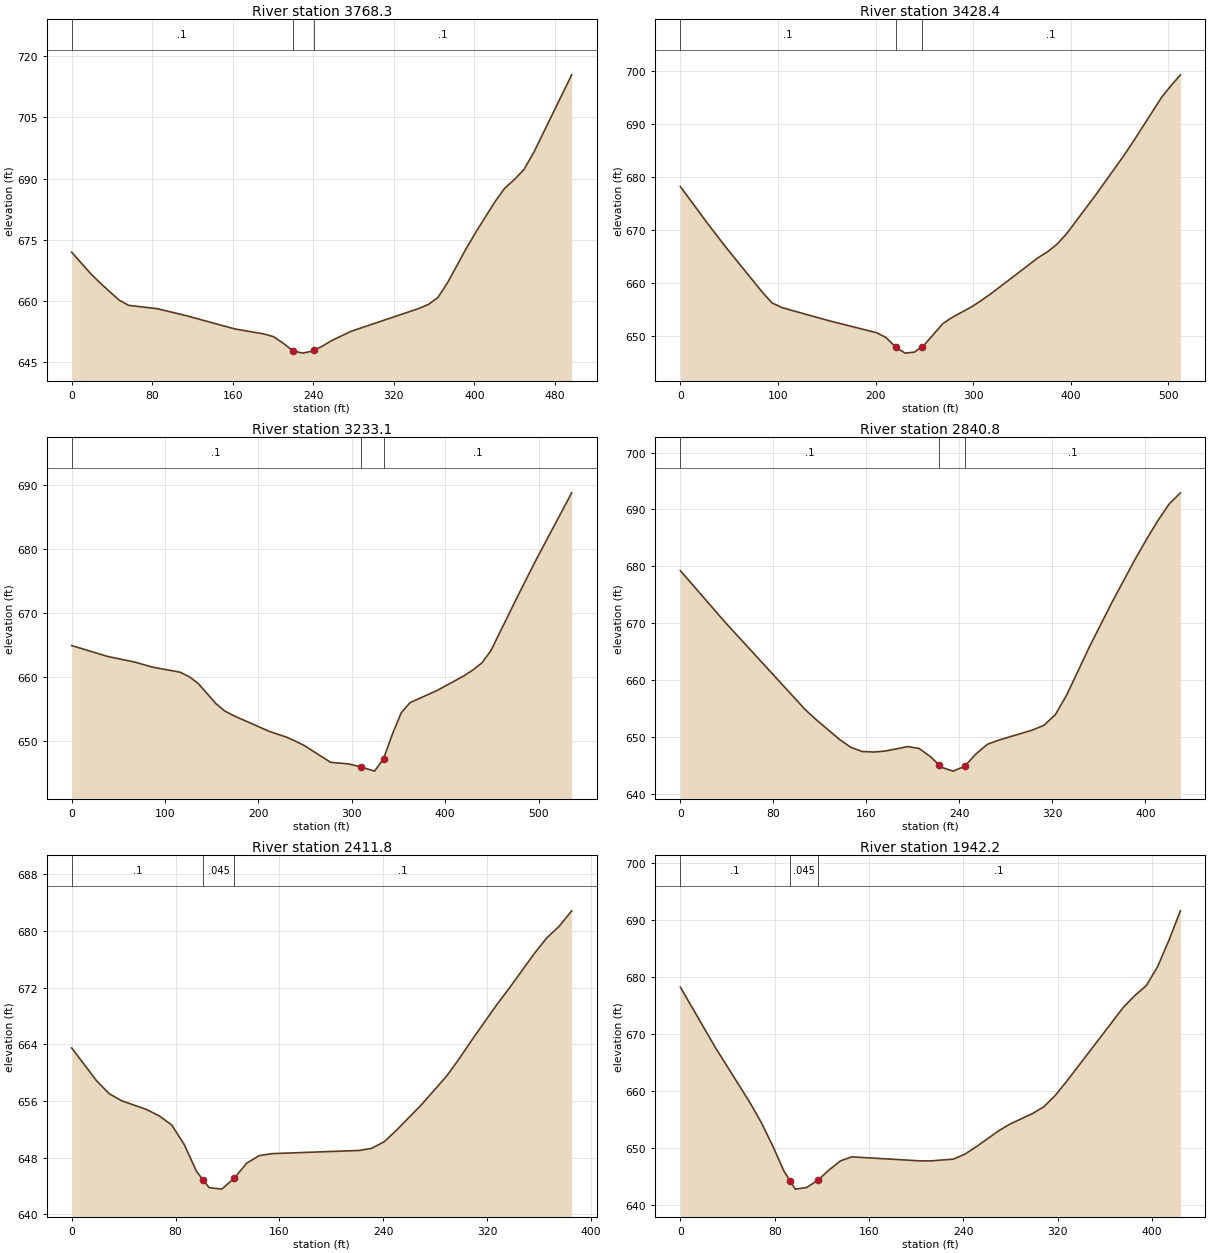
Type RM Length L Ch R = 1 ,3768.3  ,351.4,339.9,327.5
XS GIS Cut Line= 4
     1823670.724      574290.759     1823596.071      574301.175
     1823351.279      574434.856     1823252.321      574537.286
#Sta/Elev= 30
       0  671.88    18.8  666.64    28.3  664.32    47.1  660.12    56.5  658.82
      85     658   113.8  656.28   161.9  653.03   190.8  651.79   200.4  651.13
     210  649.54   219.6  647.67   229.3  647.07   238.9  647.55   240.6  647.76
   248.5  648.71   258.1  650.13   277.4  652.42   344.7  658.03   354.3  659.02
   363.8  660.74   373.3  664.35   392.3  672.95   401.8  676.93   420.8  684.41
   430.2  687.62   439.8  689.75   449.2  692.18   458.7  696.24   496.7  715.49
#Mann= 3 , 0 , 0
       0      .1       0   219.6    .045       0   240.6      .1       0
Bank Sta=219.6,240.6
XS Rating Curve= 0 ,0
Exp/Cntr=0.3,0.1

Type RM Length L Ch R = 1 ,3428.4  ,211,195.4,180.3
XS GIS Cut Line= 4
     1823398.154      573896.661     1823366.904      573985.203
     1823245.376      574184.856     1823168.987      574353.259
#Sta/Elev= 30
       0  678.15    28.2  671.13      47  666.65    84.5  658.16    93.9  656.26
   103.6  655.41   113.4  654.89   152.3   652.9     201  650.65   210.8  649.73
   220.5  647.97   230.2   646.8     240     647   247.5     648   249.7  648.29
   269.2  652.39   278.9  653.56   298.4   655.5   308.2  656.68   317.9  657.93
   366.6  664.76   376.3  665.88     386   667.3   395.8  669.26     425  676.41
   454.2   683.9   463.9  686.56   493.1  694.92   502.8  697.15   512.5  699.19
#Mann= 3 , 0 , 0
       0      .1       0   220.5    .045       0   247.5      .1       0
Bank Sta=220.5,247.5
XS Rating Curve= 0 ,0
Exp/Cntr=0.3,0.1

Type RM Length L Ch R = 1 ,3233.1  ,398.9,392.3,381.9
XS GIS Cut Line= 4
     1823083.918      573731.731     1823111.696      573874.092
      1823141.21       574089.37     1823094.335      574256.036
#Sta/Elev= 30
       0  664.91    38.7   663.2    67.7  662.32      87  661.52     116  660.75
   125.7  660.05   135.4     659   154.5  655.82   163.9  654.67   173.4  653.94
   211.2   651.5   230.1  650.57   239.5  649.95     249  649.27   277.3  646.63
   296.2  646.39   309.4  645.92   324.4  645.25     334   647.2   343.4     651
   352.9  654.37   362.3  655.97   391.2  657.87     420  660.16   429.7  661.09
   439.3  662.19   448.9   664.1   477.8  672.68     497  678.23   535.5  688.83
#Mann= 3 , 0 , 0
       0      .1       0   309.4    .045       0     334      .1       0
Bank Sta=309.4,334
XS Rating Curve= 0 ,0
Exp/Cntr=0.3,0.1

Type RM Length L Ch R = 1 ,2840.8  ,431.1,429,427
XS GIS Cut Line= 2
     1822688.085      573886.245     1822879.057      574271.661
#Sta/Elev= 30
       0  679.24    39.1  670.04   107.5   654.8   117.3  652.97   136.9  649.58
   146.6  648.19   156.4  647.46   166.2  647.37     176  647.53   195.5  648.32
   205.3     648   215.1  646.55   222.6   645.1   224.8  644.67   234.6  644.01
   244.4  644.84   254.2  647.02     264  648.72   273.7  649.45     303  651.24
   312.8  652.08   322.6  653.96   332.4  657.44   351.9  665.88   371.5  673.79
     391  681.21   400.8   684.7   410.6  688.01   420.4  690.96   430.1  692.93
#Mann= 3 , 0 , 0
       0      .1       0   222.6    .045       0   244.4      .1       0
Bank Sta=222.6,244.4
XS Rating Curve= 0 ,0
Exp/Cntr=0.3,0.1

Type RM Length L Ch R = 1 ,2411.8  ,492.4,469.6,446.5
XS GIS Cut Line= 2
     1822377.321      574186.592      1822587.39      574509.509
#Sta/Elev= 30
       0  663.49    19.3  658.83    28.9  657.03    38.5  656.03    57.8  654.79
    67.4   653.9      77  652.63    86.7  649.85    96.3  646.02   101.1  644.89
   105.9  643.76   115.6  643.55   125.2  645.08   134.8  647.21   144.5  648.28
   154.1  648.56   221.5  649.01   231.1  649.31   240.8  650.25   250.4   651.9
   269.7  655.52   288.9  659.52   298.6  661.97   308.2  664.58   327.4  669.57
   337.1  671.92   356.3  676.79     366  679.02   375.6  680.68   385.2  682.85
#Mann= 3 , 0 , 0
       0      .1       0   101.1    .045       0   125.2      .1       0
Bank Sta=101.1,125.2
XS Rating Curve= 0 ,0
Exp/Cntr=0.3,0.1

Type RM Length L Ch R = 1 ,1942.2  ,451.9,453,454.2
XS GIS Cut Line= 4
     1822066.557      574617.147      1822118.64      574644.925
     1822358.224      574646.661     1822474.543      574693.536
#Sta/Elev= 30
       0  678.19    29.5  667.65      59  657.91    68.6  654.42    78.2  650.35
    87.8   645.9      93  644.18    97.4  642.72     107     643   116.5  644.27
   126.1   646.1   135.7  647.68   145.3  648.39   202.8  647.69   212.4  647.68
   231.5  647.99   241.1  648.85   250.7  650.14   269.9  652.97   279.4  654.14
   298.6  655.99   308.3  657.21   317.9  659.18   327.6  661.67   375.8   674.7
   385.4  676.73   395.1  678.47   404.7  681.81   414.4  686.49     424   691.6
#Mann= 3 , 0 , 0
       0      .1       0      93    .045       0   116.5      .1       0
Bank Sta=93,116.5
XS Rating Curve= 0 ,0
Exp/Cntr=0.3,0.1

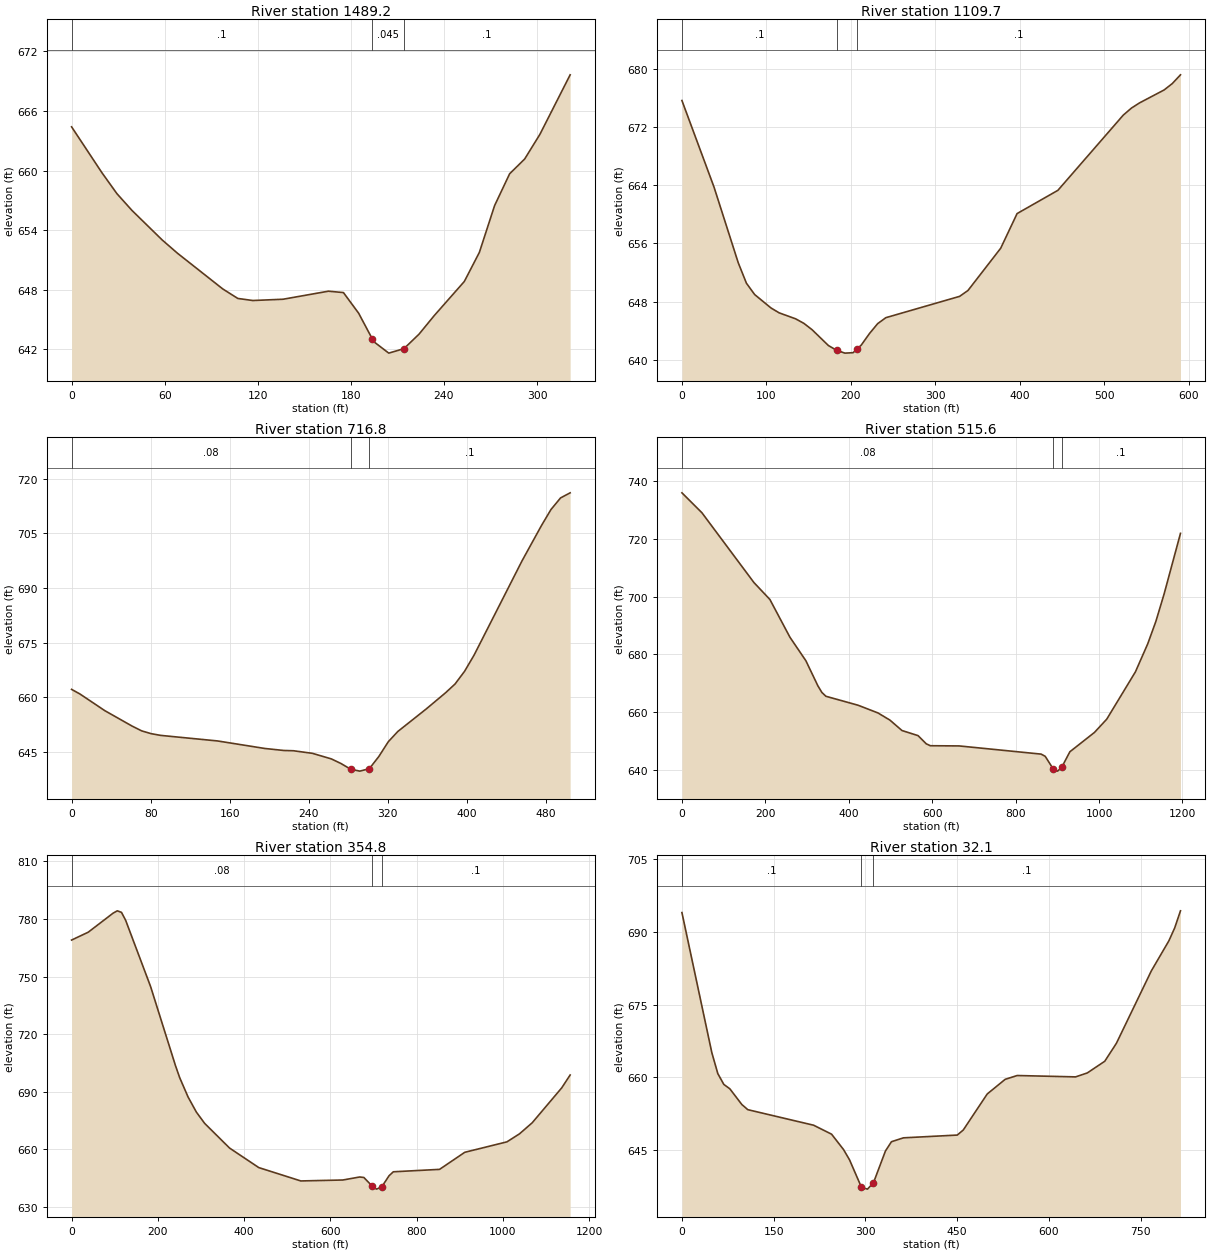
Type RM Length L Ch R = 1 ,1489.2  ,402.7,379.5,368.2
XS GIS Cut Line= 2
     1822080.446      575068.536     1822401.626      575075.481
#Sta/Elev= 26
       0   664.4    19.5  659.79    29.2  657.67    38.9  655.98    58.4     653
    68.2  651.67    97.4  648.07   107.1  647.11   116.8   646.9   136.3  647.03
   165.5  647.84   175.2   647.7     185  645.62   193.8  643.03   194.7  642.76
   204.4   641.6   214.2  642.05   223.9  643.51   233.6  645.36   253.1  648.82
   262.8  651.75   272.6  656.46   282.3  659.67     292  661.16   301.8  663.64
   321.3  669.64
#Mann= 3 , 0 , 0
       0      .1       0   193.8    .045       0   214.2      .1       0
Bank Sta=193.8,214.2
XS Rating Curve= 0 ,0
Exp/Cntr=0.3,0.1

Type RM Length L Ch R = 1 ,1109.7  ,340.4,392.9,425
XS GIS Cut Line= 4
      1822085.22      575463.502     1822139.474      575480.863
     1822449.803      575400.568     1822662.477      575409.248
#Sta/Elev= 30
       0  675.62      38  663.73    66.7  653.33    76.4  650.52    86.1  648.97
   105.5  647.12   115.2  646.45   134.7  645.63   144.4  645.01   154.1  644.14
   173.5  641.96   183.2  641.31     193  640.92   202.7  640.98   207.5   641.5
   212.4  642.03   222.1  643.61   231.8  644.97   241.5  645.79   328.9  648.72
   338.7  649.52   377.5  655.33   396.9  660.09   445.2  663.28   522.6  673.61
   532.3  674.58     542   675.3     571  677.07   580.7  677.95   590.4  679.15
#Mann= 3 , 0 , 0
       0      .1       0   183.2    .045       0   207.5      .1       0
Bank Sta=183.2,207.5
XS Rating Curve= 0 ,0
Exp/Cntr=0.3,0.1

Type RM Length L Ch R = 1 ,716.8   ,212.6,201.2,195.4
XS GIS Cut Line= 4
      1822078.71      575550.307     1822102.581      575585.029
     1822276.192      575849.786     1822356.487      575971.314
#Sta/Elev= 30
       0  662.17     8.4  660.91    33.7  656.31    61.3  652.07    70.9  650.77
    80.5     650    90.1  649.53   147.7     648   195.6  645.93   214.8  645.38
   224.4  645.31   243.6   644.6   262.8  643.07   272.4  641.82   282.4  640.23
   291.6  639.71   301.2  640.37   310.8  643.71   320.4  647.78     330  650.59
   358.7  656.77   378.2   661.2   387.9  663.63   397.6  667.14   407.3  671.63
   455.8  697.52   475.3  707.14     485  711.58   494.7  714.77   504.4  716.17
#Mann= 3 , 0 , 0
       0     .08       0   282.4    .045       0   301.2      .1       0
Bank Sta=282.4,301.2
XS Rating Curve= 0 ,0
Exp/Cntr=0.3,0.1

Type RM Length L Ch R = 1 ,515.6   ,168.4,160.7,152.6
XS GIS Cut Line= 5
     1821573.067        575274.7     1821745.369      575396.337
     1821872.546      575717.408     1822185.046      576016.887
      1822391.21      576021.227
#Sta/Elev= 30
       0  735.86    47.9  728.98   172.6  704.86   210.9     699   258.9  685.96
   297.2  677.82     326  669.14   335.6  666.86   345.2  665.54     422  662.46
   469.9  659.79   498.7   657.3   527.5  653.71   566.1  651.94   585.8  649.11
   595.6  648.45   664.5  648.38   861.2  645.55     871  644.79   889.9  640.47
   900.6  639.67   910.4  640.95   930.1  646.36   989.1  653.05  1018.5  657.63
  1087.3  673.99  1116.7  683.64  1136.4  691.47    1156  700.88  1195.3  721.85
#Mann= 3 , 0 , 0
       0     .08       0   889.9    .045       0   910.4      .1       0
Bank Sta=889.9,910.4
XS Rating Curve= 0 ,0
Exp/Cntr=0.3,0.1

Type RM Length L Ch R = 1 ,354.8   ,331.9,322.7,311.5
XS GIS Cut Line= 4
     1821323.501      575943.102     1821737.998      575947.443
     1822217.599      576164.456     1822432.442      576173.137
#Sta/Elev= 30
       0  769.02    38.6  773.11    96.4  783.05     106  784.24   115.7  783.44
   125.3  779.33   183.2   744.8     241  703.54   250.6  697.38   269.9  687.37
   289.2  679.46   308.5  673.55   366.3  660.69     434  650.52   531.5  643.56
     629  644.05     668  645.62   677.7  645.36   697.2  640.82     707   639.3
     719  640.43   736.2  646.29     746  648.33   853.2  649.59   911.7  658.48
  1009.4  663.92  1038.7  668.12    1068  673.85  1136.4  692.02    1156  698.74
#Mann= 3 , 0 , 0
       0     .08       0   697.2    .045       0     719      .1       0
Bank Sta=697.2,719
XS Rating Curve= 0 ,0
Exp/Cntr=0.3,0.1

Type RM Length L Ch R = 1 ,32.1    ,23.8,32.1,41.1
XS GIS Cut Line= 4
     1821653.362      576335.897     1822132.963      576335.897
     1822211.088      576329.387     1822438.953      576210.029
#Sta/Elev= 30
       0  693.94    48.9  665.09    58.7  660.78    68.5  658.56    78.3  657.66
    97.9  654.43   107.7  653.36   215.3  650.16   244.7  648.31   264.3  645.14
   274.1  643.02   293.6  637.36   303.4     637   313.2  638.32   332.8  644.86
   342.6  646.76   362.2  647.56   450.2  648.13     460  649.17   499.2  656.59
   528.6  659.61   548.2  660.39   643.7  660.11   662.8  660.92   691.4  663.33
   710.4  667.02   767.6  681.95   796.2  688.12   805.7  690.77   815.2   694.3
#Mann= 3 , 0 , 0
       0      .1       0   293.6    .045       0   313.2      .1       0
Bank Sta=293.6,313.2
XS Rating Curve= 0 ,0
Exp/Cntr=0.3,0.1

Chan Stop Cuts=-1
Use User Specified Reach Order=0
Composite Channel Slope=5